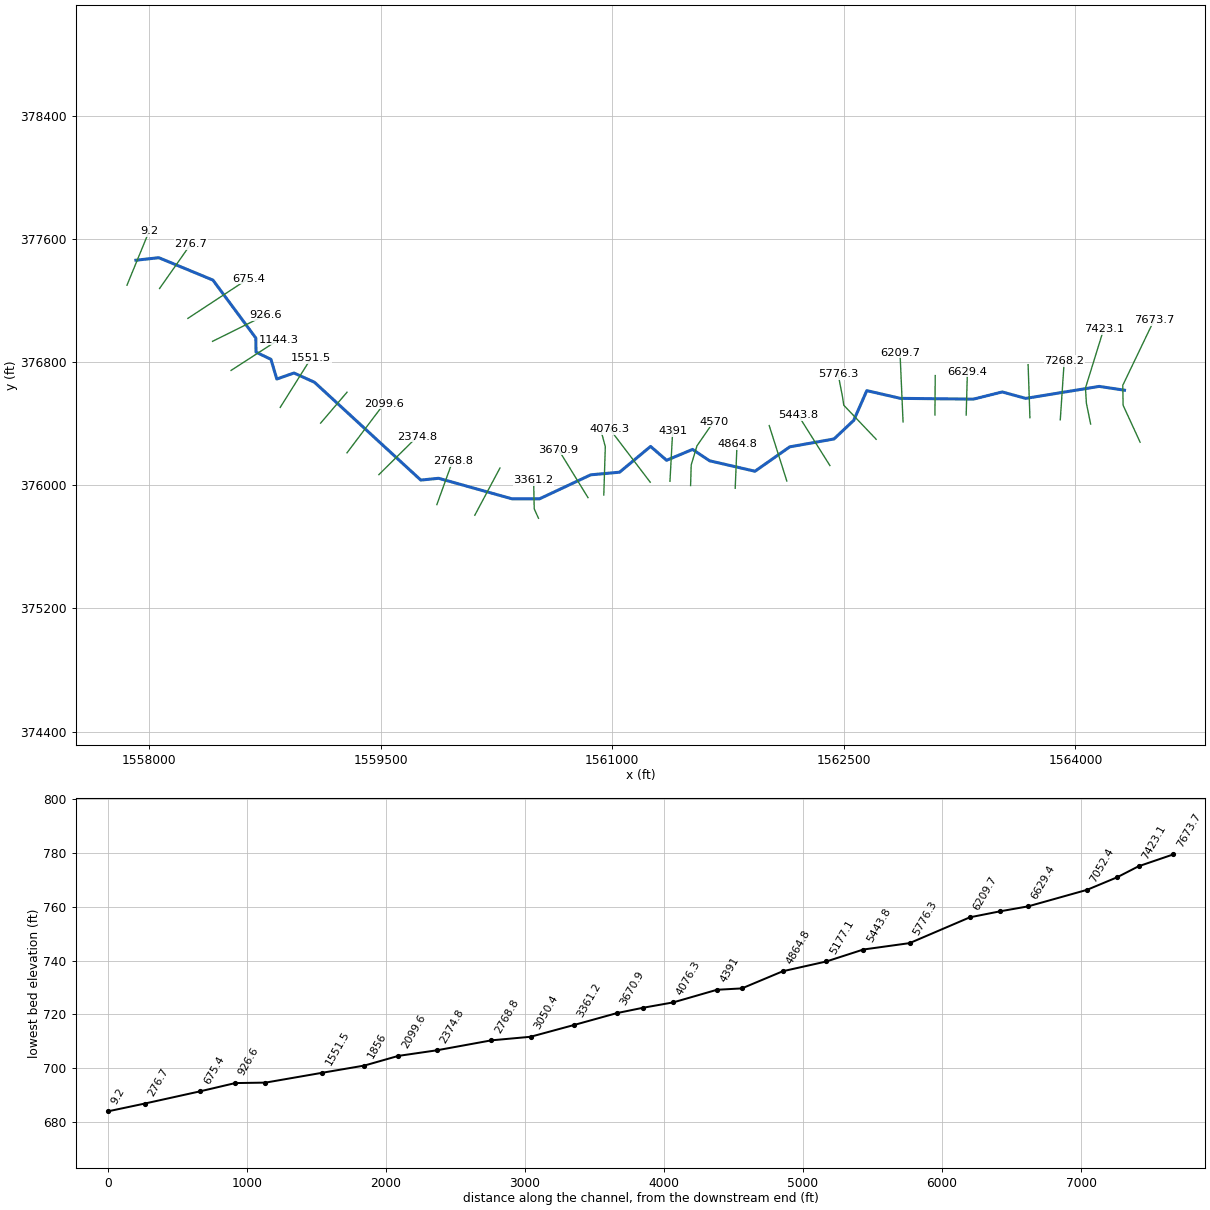
--- BIGBRANCH.prj (project) ---

Proj Title=BIGBRANCH
Current Plan=p01
Default Exp/Contr=0,0
English Units
Geom File=g01
Flow File=f01
Plan File=p01
BEGIN DESCRIPTION:
END DESCRIPTION:
DSS Export Rating Curves= 0
DSS Export Rating Curve Sorted= 0
DSS Export Volume Flow Curves= 0
DXF OffsetX= 0
DXF OffsetY= 0
DXF ScaleX= 0
DXF ScaleY= 0

--- BIGBRANCH.p01 (plan) ---

Plan Title=Floodplain
Program Version=4.00
Geom File=g01
Flow File=f01
K Sum by GR=0
Std Step Tol=0.01
Critical Tol=0.01
Num of Std Step Trials=20
Max Error Tol=0.3
Flow Tol Ratio=0.001
Split Flow NTrial=30
Split Flow Tol=0.02
Split Flow Ratio=0.02
Log Output Level=0
Friction Slope Method=1
Unsteady Friction Slope Method=2
Unsteady Bridges Friction Slope Method=1
Global Log Level=0
CheckData=False
Run HTab=0
Run UNet=0
Run PostProcess=0
UNET Theta=0
UNET Theta Warmup=0
UNET ZTol=0
UNET ZSATol=0
UNET MxIter=0
UNET MaxInSteps=0
UNET DtIC=0
UNET DtMin=0
UNET MaxCRTS=0
UNET WFStab=0
UNET SFStab=0
UNET WFX=0
UNET SFX=0
UNET DSS MLevel=0
UNET DZMax Abort=0
UNET Convert EG Bridges=0
UNET Use Existing IB Tables=0
UNET Froude Limit=0
UNET Froude Power=0
Write IC File=0
Echo Input=False
Echo Output=False
Write Detailed=0

--- BIGBRANCH.f01 (steady flow) ---

Flow Title=NFF Regression Equation
Program Version=4.00
Number of Profiles=1
Profile Names=P100yr
River Rch & RM=BIGBRANCH,Main      ,7673.7
399.4256
River Rch & RM=BIGBRANCH,Main      ,7268.2
419.7665
River Rch & RM=BIGBRANCH,Main      ,5776.3
459.5068
River Rch & RM=BIGBRANCH,Main      ,4570
498.1372
River Rch & RM=BIGBRANCH,Main      ,2768.8
533.4703
River Rch & RM=BIGBRANCH,Main      ,675.4
583.9390
Boundary for River Rch & Prof#=BIGBRANCH,Main      ,1
Up Type=0
Dn Type=3
Dn Slope=0.011527

--- BIGBRANCH.g01 (geometry) ---

Geom Title=Geometry
Program Version=4.00

River Reach=BIGBRANCH       ,Main
Reach XY= 30
     1564318.185      376616.848     1564154.559      376641.609
     1563678.085      376563.727     1563526.116      376605.592
     1563339.578      376558.911      1562866.34      376563.962
     1562648.638      376613.995     1562563.983      376421.244
      1562436.35      376300.464     1562149.231      376249.104
     1561924.093      376090.871     1561630.342      376158.595
     1561519.526      376232.568     1561351.596       376161.93
     1561247.593      376251.917     1561046.941      376084.649
     1560859.541      376067.485     1560528.185      375911.741
     1560349.982      375911.779     1559874.396      376045.124
     1559758.892        376033.4     1559070.065      376668.502
     1558937.457      376728.534     1558825.928      376689.403
     1558788.098      376817.273     1558691.217      376863.999
     1558690.159       376955.53     1558412.173      377331.657
     1558061.543      377476.974     1557913.013       377460.66

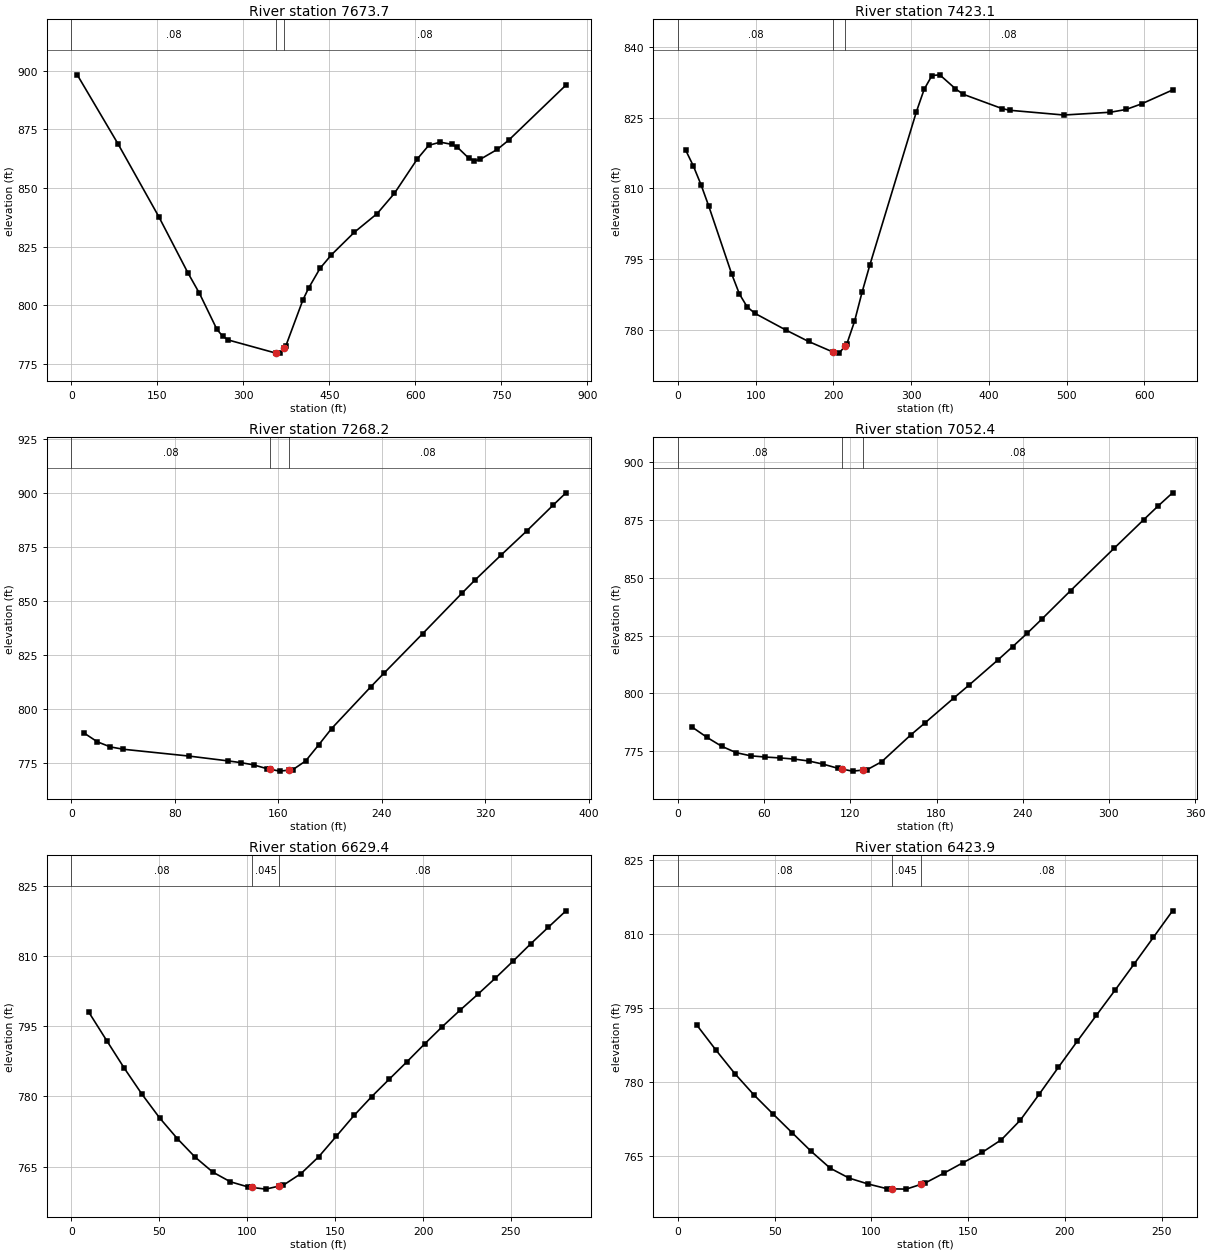
Type RM Length L Ch R = 1 ,7673.7  ,249.6,250.6,251.6
XS GIS Cut Line= 4
     1564419.367      376279.243     1564309.243      376519.155
     1564307.277      376648.944     1564509.826      377071.742
#Sta/Elev= 30
    10.2  898.23    81.2  868.83   152.3  837.79   203.1  813.84   223.4  805.01
   253.8  789.68     264  786.72     274  785.13   356.3  779.58   363.8  779.55
   371.3  781.76   373.8   782.5   403.8  802.25   413.7  807.27   433.7  815.73
   453.6   821.5   493.5  831.09   533.4  839.08   563.4  847.69   603.3  862.35
   623.2  868.15   643.2  869.52   663.1   868.6   673.1  867.38     693  862.69
     703  861.56     713   862.2   742.9  866.44   762.8  870.39   862.6  893.85
#Mann= 3 , 0 , 0
       0     .08       0   356.3    .045       0   371.3     .08       0
Bank Sta=356.3,371.3
XS Rating Curve= 0 ,0
Exp/Cntr=0.3,0.1

Type RM Length L Ch R = 1 ,7423.1  ,157.7,154.9,152.1
XS GIS Cut Line= 4
     1564098.828      376397.233     1564071.297      376532.921
     1564065.397      376631.246     1564183.387      377012.747
#Sta/Elev= 30
     9.9   818.1    19.8  814.74    29.7  810.76    39.6  806.25    69.2  791.84
    79.1  787.62      89  784.92    98.9  783.55   138.5  780.04     168  777.59
   199.9  775.32   207.4  775.12   214.9  776.61   217.3  777.08   227.1  781.82
     237   788.1   246.9   793.8   306.8  826.25   316.8     831   326.8  833.89
   336.8  834.04   356.8  831.12   366.7  829.94   416.7  826.91   426.6  826.54
   496.5  825.53   556.4  826.12   576.4   826.7   596.4  827.89   636.3  830.83
#Mann= 3 , 0 , 0
       0     .08       0   199.9    .045       0   214.9     .08       0
Bank Sta=199.9,214.9
XS Rating Curve= 0 ,0
Exp/Cntr=0.3,0.1

Type RM Length L Ch R = 1 ,7268.2  ,213.6,215.8,218.1
XS GIS Cut Line= 2
     1563902.178      376424.763     1563927.742      376806.264
#Sta/Elev= 25
    10.1  788.56    20.1  784.59    30.2  782.23    40.2  781.15    90.6  778.01
   120.7  775.78   130.8  774.96   140.9   773.9   150.9  772.19   153.5  771.89
     161     771   168.5  771.48   171.1  771.64   181.1  775.71   191.2  783.18
   201.2  790.78   231.4  810.08   241.5  816.36   271.7  834.87   301.9  853.55
   311.9   859.6     332  871.17   352.2  882.56   372.3  894.37   382.4  900.18
#Mann= 3 , 0 , 0
       0     .08       0   153.5    .045       0   168.5     .08       0
Bank Sta=153.5,168.5
XS Rating Curve= 0 ,0
Exp/Cntr=0.3,0.1

Type RM Length L Ch R = 1 ,7052.4  ,424.3,422.9,421.6
XS GIS Cut Line= 2
     1563705.528      376438.529     1563693.729      376782.666
#Sta/Elev= 29
    10.1   785.3    20.3  780.92    30.4  777.11    40.5  774.34    50.6  772.97
    60.8  772.44    70.9  772.06      81  771.55    91.1  770.72   101.3  769.32
   111.4  767.56     114  767.24   121.5  766.34     129   766.8   131.7  766.97
   141.8   770.4     162  781.98   172.2  787.35   192.4  798.19   202.6  803.58
   222.8  814.52   232.9  820.18   243.1  826.03   253.2   832.1   273.4  844.54
   303.8  862.94   324.1  875.13   334.2  881.11   344.3  886.84
#Mann= 3 , 0 , 0
       0     .08       0     114    .045       0     129     .08       0
Bank Sta=114,129
XS Rating Curve= 0 ,0
Exp/Cntr=0.3,0.1

Type RM Length L Ch R = 1 ,6629.4  ,205.2,205.6,206
XS GIS Cut Line= 2
     1563292.563      376456.227     1563300.429      376737.437
#Sta/Elev= 30
      10  797.93    20.1  791.91    30.1  786.02    40.2  780.44    50.2   775.4
    60.3  770.97    70.3  767.06    80.4  763.84    90.4  761.77   100.5  760.67
     103  760.55   110.5   760.2     118  760.84   120.6  761.06   130.6  763.52
   140.7  767.13   150.7   771.5   160.8  775.95   170.8  779.96   180.8  783.69
   190.9  787.42   200.9  791.21     211  794.92     221   798.4   231.1  801.79
   241.1  805.25   251.2  808.89   261.2  812.58   271.3  816.15   281.3  819.64
#Mann= 3 , 0 , 0
       0     .08       0     103    .045       0     118     .08       0
Bank Sta=103,118
XS Rating Curve= 0 ,0
Exp/Cntr=0.3,0.1

Type RM Length L Ch R = 1 ,6423.9  ,213,214.2,215.4
XS GIS Cut Line= 2
     1563090.014      376456.227      1563091.98      376711.872
#Sta/Elev= 28
     9.8  791.51    19.7  786.44    29.5  781.66    39.3  777.39    49.2  773.51
      59  769.74    68.8  765.99    78.7  762.55    88.5  760.54    98.3  759.35
   108.2  758.38   110.5  758.37     118  758.31   125.5  759.26   127.8  759.55
   137.7  761.59   147.5  763.69   157.3  765.76   167.2  768.31     177  772.28
   186.8  777.56   196.7     783   206.5   788.3   216.3  793.51   226.2  798.73
     236     804   245.8  809.31   255.7  814.68
#Mann= 3 , 0 , 0
       0     .08       0   110.5    .045       0   125.5     .08       0
Bank Sta=110.5,125.5
XS Rating Curve= 0 ,0
Exp/Cntr=0.3,0.1

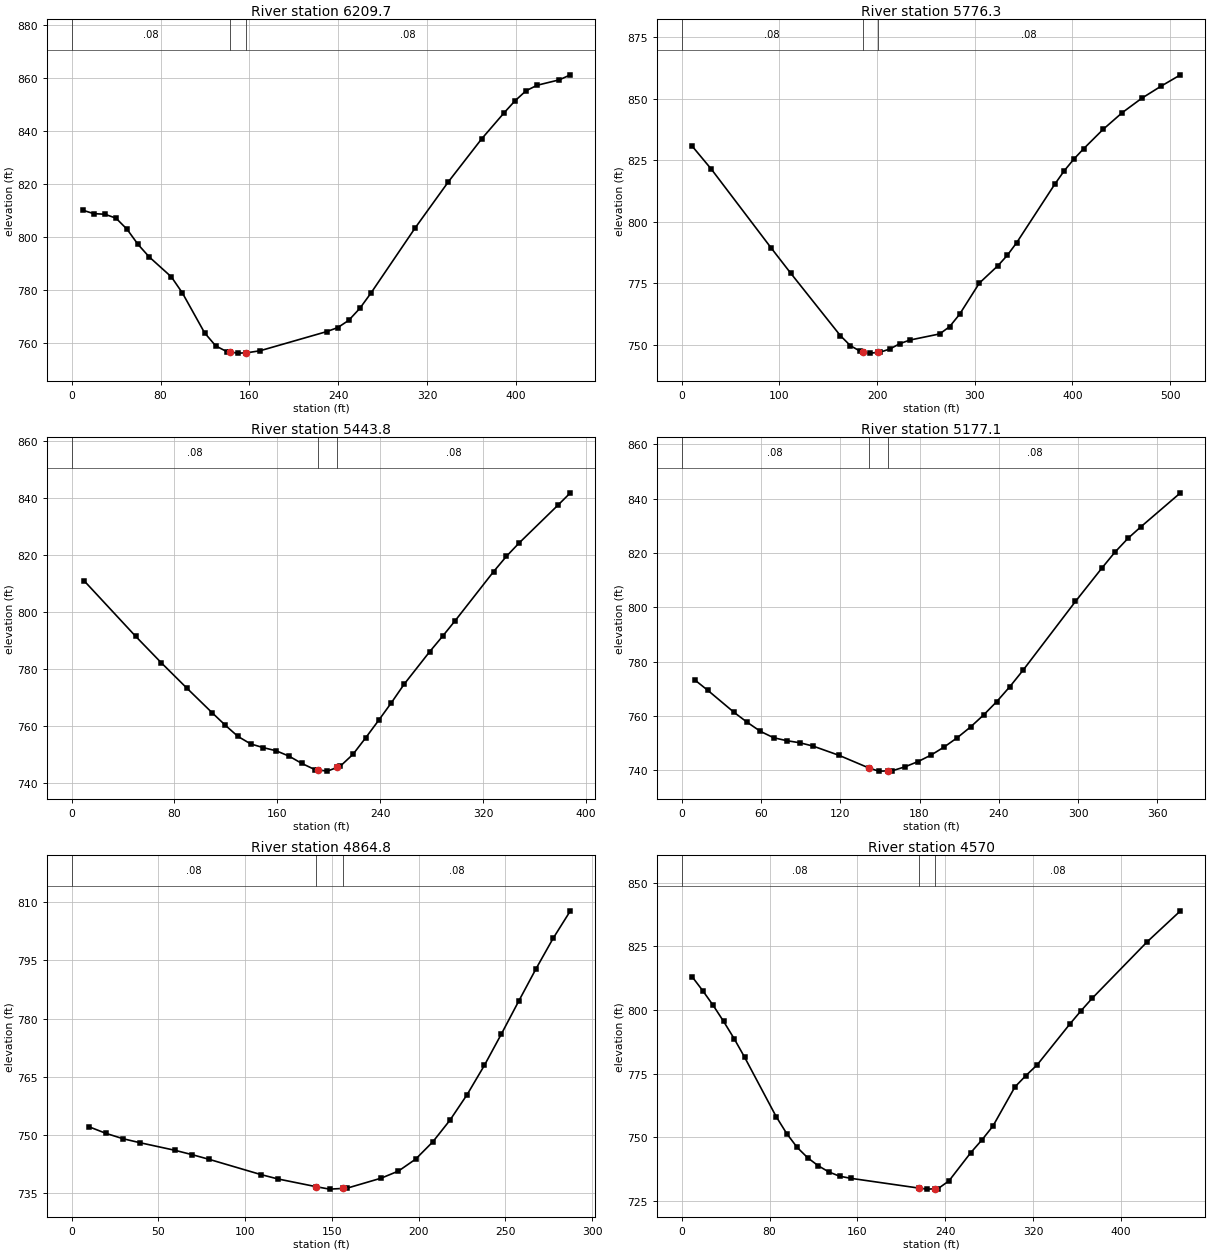
Type RM Length L Ch R = 1 ,6209.7  ,417,433.3,448.7
XS GIS Cut Line= 2
     1562883.531      376410.998     1562863.866       376859.36
#Sta/Elev= 30
      10  810.15    19.9  808.86    29.9  808.62    39.9  807.16    49.9  802.94
    59.8  797.19    69.8   792.5    89.8  784.92    99.7  778.85   119.7  763.76
   129.7  758.84   139.6  756.69   142.1  756.55   149.6  756.11   157.1   756.2
   169.5     757   229.4  764.23   239.4  765.75   249.3  768.49   259.3  773.01
   269.3  778.79   309.2   803.5   339.1  820.95     369  837.15     389   846.9
   398.9  851.49   408.9  855.31   418.9   857.4   438.8  859.44   448.8  861.34
#Mann= 3 , 0 , 0
       0     .08       0   142.1    .045       0   157.1     .08       0
Bank Sta=142.1,157.1
XS Rating Curve= 0 ,0
Exp/Cntr=0.3,0.1

Type RM Length L Ch R = 1 ,5776.3  ,336.5,332.5,329.5
XS GIS Cut Line= 4
      1562709.32      376298.372     1562499.457       376519.28
     1562490.955      376575.873     1562462.608      376721.842
#Sta/Elev= 30
    10.2  831.01    30.5  821.31    91.4  789.41   111.7  778.99   162.5  753.59
   172.7  749.54   182.8  747.26   185.5  747.06     193   746.5   200.5  746.77
   203.1  746.86   213.3  748.22   223.4  750.37   233.6  751.82   264.1  754.32
   274.2  757.25   284.4  762.26   304.7  775.01   323.8  782.12   333.3  786.31
   342.9  791.45   381.8  815.19   391.7  820.78   401.6  825.54   411.5  829.72
   431.3  837.55   451.1  844.43     471  850.26   490.8  855.19   510.6  859.79
#Mann= 3 , 0 , 0
       0     .08       0   185.5    .045       0   200.5     .08       0
Bank Sta=185.5,200.5
XS Rating Curve= 0 ,0
Exp/Cntr=0.3,0.1

Type RM Length L Ch R = 1 ,5443.8  ,272.5,266.7,259.3
XS GIS Cut Line= 2
     1562409.605      376127.822     1562203.123      376456.227
#Sta/Elev= 30
     9.9  810.83    49.7  791.48    69.6  782.21    89.5   773.3   109.4  764.56
   119.4  760.28   129.3  756.32   139.3  753.66   149.2  752.35   159.1  751.26
   169.1  749.38     179  746.83     189  744.69   191.4  744.55   198.9  744.12
   206.4  745.41   208.9  745.84   218.8     750   228.8  755.87   238.7  761.89
   248.7  768.13   258.6  774.62   278.5  786.05   288.5  791.45   298.4  796.97
   328.2  814.15   338.2  819.52   348.1  824.21     378  837.35   387.9  841.78
#Mann= 3 , 0 , 0
       0     .08       0   191.4    .045       0   206.4     .08       0
Bank Sta=191.4,206.4
XS Rating Curve= 0 ,0
Exp/Cntr=0.3,0.1

Type RM Length L Ch R = 1 ,5177.1  ,320.1,312.3,306.2
XS GIS Cut Line= 2
     1562130.362      376027.531     1562016.305        376387.4
#Sta/Elev= 30
     9.9  773.24    19.9  769.35    39.7  761.27    49.7   757.6    59.6   754.3
    69.5  751.97    79.5  750.87    89.4   750.1    99.3   748.9   119.2  745.45
   141.5  740.86     149  739.66   156.5  739.72     159  739.74   168.9  741.23
   178.8  743.16   188.8  745.59   198.7  748.56   208.6  751.98   218.6  755.91
   228.5  760.33   238.4  765.23   248.4  770.78   258.3  776.77     298  802.12
   317.9  814.34   327.8  820.22   337.8  825.38   347.7  829.68   377.5  842.12
#Mann= 3 , 0 , 0
       0     .08       0   141.5    .045       0   156.5     .08       0
Bank Sta=141.5,156.5
XS Rating Curve= 0 ,0
Exp/Cntr=0.3,0.1

Type RM Length L Ch R = 1 ,4864.8  ,301,294.8,288.6
XS GIS Cut Line= 2
     1561796.057      375980.335     1561807.856      376267.444
#Sta/Elev= 25
     9.9  752.13    19.8  750.41    29.7  749.02    39.6  747.98    59.5  746.05
    69.4  744.93    79.3  743.71     109   739.8   118.9  738.66   141.1  736.65
   148.6  736.04   156.1  736.21   158.5  736.26   178.4  738.87   188.3  740.69
   198.2  743.76   208.1  748.21     218   753.8   227.9   760.4   237.8   767.9
   247.7  776.07   257.6  784.47   267.5  792.75   277.4  800.63   287.4  807.76
#Mann= 3 , 0 , 0
       0     .08       0   141.1    .045       0   156.1     .08       0
Bank Sta=141.1,156.1
XS Rating Curve= 0 ,0
Exp/Cntr=0.3,0.1

Type RM Length L Ch R = 1 ,4570    ,173.5,179,184.5
XS GIS Cut Line= 4
     1561506.982      375998.033     1561510.915      376131.755
     1561548.278      376255.645     1561656.436      376412.964
#Sta/Elev= 30
     9.6  812.97    19.1  807.58    28.7  801.76    38.2  795.46    47.8  788.68
    57.3  781.41      86  758.12    95.6  751.46   105.1  746.03   114.7  741.95
   124.2  738.85   133.8  736.42   143.7  734.72   153.7   733.9   215.9  730.05
   223.4  729.64   230.9  729.77   233.3  729.81   243.3  732.86   263.2  743.97
   273.2  748.89   283.3  754.35   303.4  769.77   313.4  774.23   323.5  778.36
   353.6  794.57   363.7  799.73   373.7  804.56   423.9  826.79   454.1   838.9
#Mann= 3 , 0 , 0
       0     .08       0   215.9    .045       0   230.9     .08       0
Bank Sta=215.9,230.9
XS Rating Curve= 0 ,0
Exp/Cntr=0.3,0.1

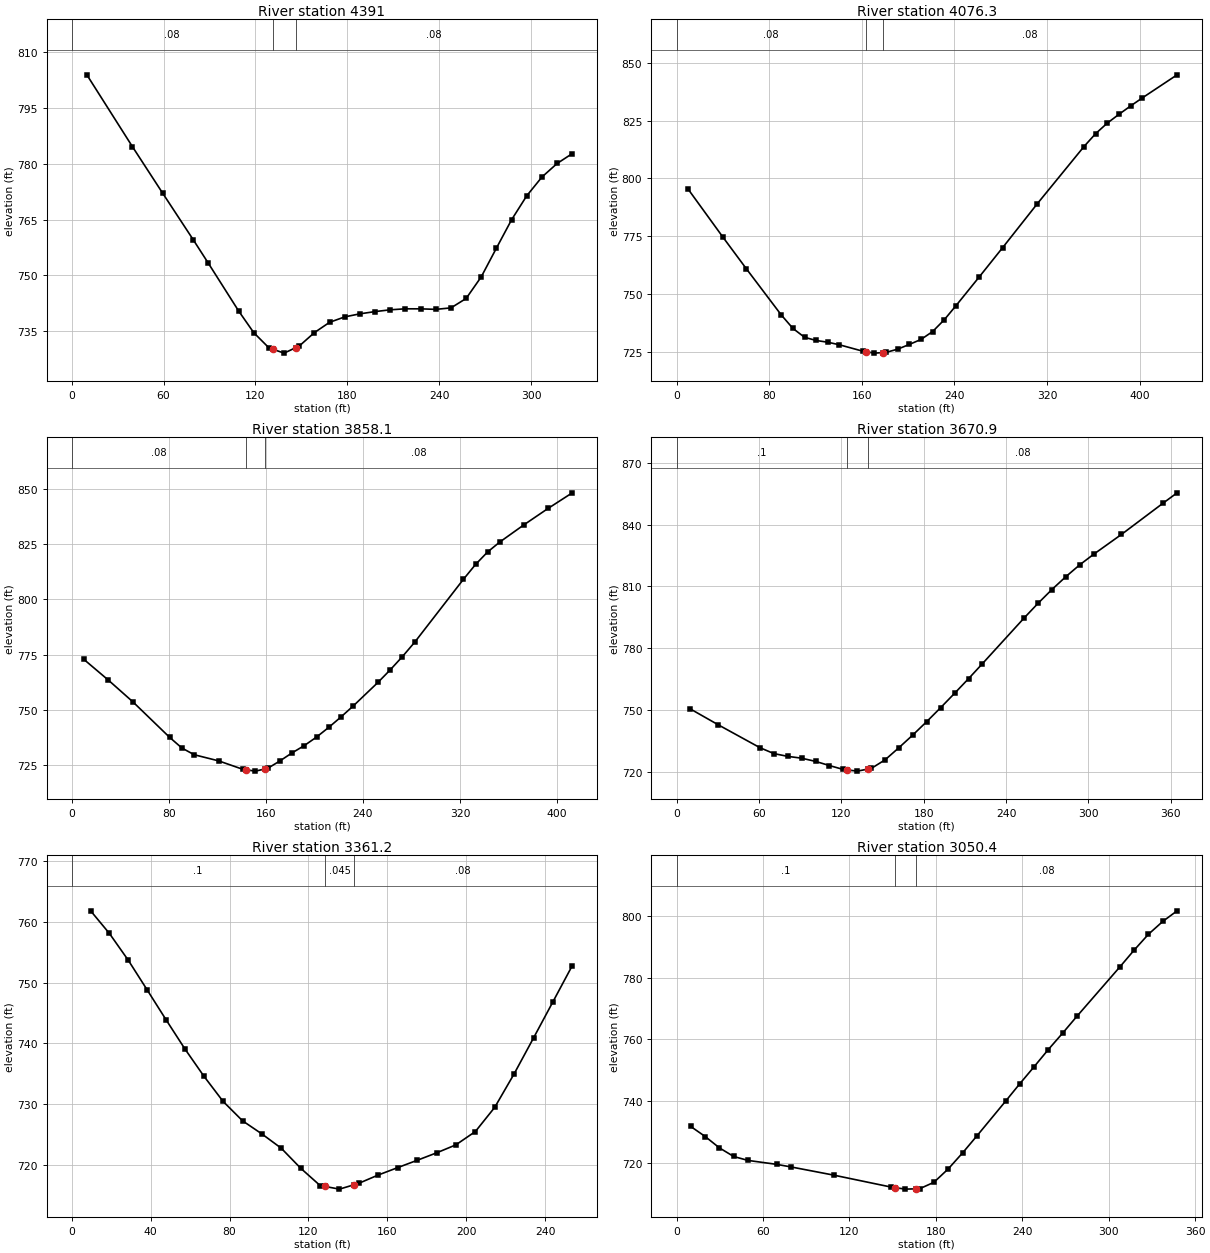
Type RM Length L Ch R = 1 ,4391    ,298.5,314.7,330.8
XS GIS Cut Line= 2
      1561373.26      376025.564     1561390.959      376352.003
#Sta/Elev= 30
     9.9  803.85    39.6   784.6    59.4  772.08    79.3  759.62    89.2  753.29
     109  740.46   118.9  734.62   128.8  730.55   131.2   730.2   138.7  729.13
   146.2  730.57   148.6  731.04   158.5  734.64   168.4   737.4   178.3  738.86
   188.2  739.68   198.1  740.28     208  740.76   217.9  741.03   227.9  741.02
   237.8  740.88   247.7  741.28   257.6  743.81   267.5  749.64   277.4  757.35
   287.3  764.96   297.2  771.39   307.1  776.41     317  780.05   326.9   782.7
#Mann= 3 , 0 , 0
       0     .08       0   131.2    .045       0   146.2     .08       0
Bank Sta=131.2,146.2
XS Rating Curve= 0 ,0
Exp/Cntr=0.3,0.1

Type RM Length L Ch R = 1 ,4076.3  ,233.7,218.2,202.8
XS GIS Cut Line= 2
     1561245.438      376019.665     1560983.893      376363.802
#Sta/Elev= 30
    10.1  795.31    40.2  774.51    60.3  760.92    90.5  740.91   100.5  735.12
   110.6  731.26   120.6   729.9   130.7  729.14   140.7  728.03   160.8  725.27
   163.4  725.05   170.9  724.43   178.4  724.67   180.9  724.74     191  726.16
     201  728.18   211.1  730.36   221.1  733.75   231.2  738.87   241.3  744.95
   261.4  757.41   281.5  770.01   311.6  789.11   351.8  813.78   361.9  819.38
   371.9  823.91     382  827.73     392  831.32   402.1   834.8   432.2  844.81
#Mann= 3 , 0 , 0
       0     .08       0   163.4    .045       0   178.4     .08       0
Bank Sta=163.4,178.4
XS Rating Curve= 0 ,0
Exp/Cntr=0.3,0.1

Type RM Length L Ch R = 1 ,3858.1  ,174,187.1,200.3
XS GIS Cut Line= 3
     1560944.563      375937.072     1560954.396      376249.745
     1560928.831      376346.103
#Sta/Elev= 30
    10.1  772.84    30.3  763.47    50.5  753.66    80.7  737.67    90.8  732.86
   100.9  729.83   121.1  727.05   141.3  723.19   143.9  722.99   151.4  722.42
   158.9  723.35   161.5  723.67   171.6  727.03   181.6  730.66   191.7  733.96
   201.8  737.81   211.9   742.2     222  746.92   232.1  751.89   252.3  762.44
   262.4  768.09   272.5  774.11   282.6  780.59   322.8  809.03   332.8  815.73
   342.7  821.35   352.7  825.83   372.6   833.6   392.6  841.04   412.5  848.07
#Mann= 3 , 0 , 0
       0     .08       0   143.9    .045       0   158.9     .08       0
Bank Sta=143.9,158.9
XS Rating Curve= 0 ,0
Exp/Cntr=0.3,0.1

Type RM Length L Ch R = 1 ,3670.9  ,321.7,309.7,297.7
XS GIS Cut Line= 2
     1560842.305      375919.373     1560651.555       376230.08
#Sta/Elev= 30
    10.1  750.59    30.4  742.91    60.8   731.8    70.9  728.95      81   727.6
    91.1  726.72   101.3  725.16   111.4  723.14   121.5  721.24   124.2  721.03
   131.7  720.44   139.2   721.4   141.8  721.73   151.9  725.91     162  731.81
   172.2  738.02   182.3   744.5   192.4  751.23   202.5  758.16   212.7  765.28
   222.8  772.55   253.2  794.73   263.3  801.82   273.4  808.51   283.6  814.77
   293.7  820.51   303.8  825.61   324.1  835.26   354.5  850.47   364.6  855.43
#Mann= 3 , 0 , 0
       0      .1       0   124.2    .045       0   139.2     .08       0
Bank Sta=124.2,139.2
XS Rating Curve= 0 ,0
Exp/Cntr=0.3,0.1

Type RM Length L Ch R = 1 ,3361.2  ,322.3,310.8,299.3
XS GIS Cut Line= 3
     1560521.392      375785.772     1560493.861      375846.734
     1560489.928      376033.551
#Sta/Elev= 28
     9.6  761.83    19.1  758.11    28.7  753.68    38.2  748.83    47.8   743.9
    57.3  739.12    66.9  734.64    76.7  730.45    86.6  727.24    96.4  725.08
   106.2  722.73   116.1  719.42   125.9  716.58   128.2  716.44   135.7  715.99
   143.2  716.72   145.6  716.96   155.4  718.32   165.2  719.53   175.1  720.74
   184.9  721.96   194.7  723.28   204.6  725.48   214.4  729.46   224.2  734.96
   234.1  740.91   243.9  746.85   253.7   752.8
#Mann= 3 , 0 , 0
       0      .1       0   128.2    .045       0   143.2     .08       0
Bank Sta=128.2,143.2
XS Rating Curve= 0 ,0
Exp/Cntr=0.3,0.1

Type RM Length L Ch R = 1 ,3050.4  ,278.4,281.6,284.7
XS GIS Cut Line= 2
     1560108.801      375805.316     1560272.021       376112.09
#Sta/Elev= 28
     9.9  731.88    19.9  728.64    29.8  724.96    39.7  722.18    49.6  720.91
    69.5  719.64    79.4  718.81   109.2  716.15   148.9   712.3   151.4  712.13
   158.9  711.63   166.4  711.73   168.8  711.76   178.7  713.84   188.6  718.15
   198.6  723.34   208.5  728.82   228.4  740.03   238.3  745.69   248.2  751.17
   258.1  756.75   268.1  762.08     278  767.52   307.8  783.47   317.7   788.9
   327.6  794.01   337.6  798.18   347.5  801.59
#Mann= 3 , 0 , 0
       0      .1       0   151.4    .045       0   166.4     .08       0
Bank Sta=151.4,166.4
XS Rating Curve= 0 ,0
Exp/Cntr=0.3,0.1

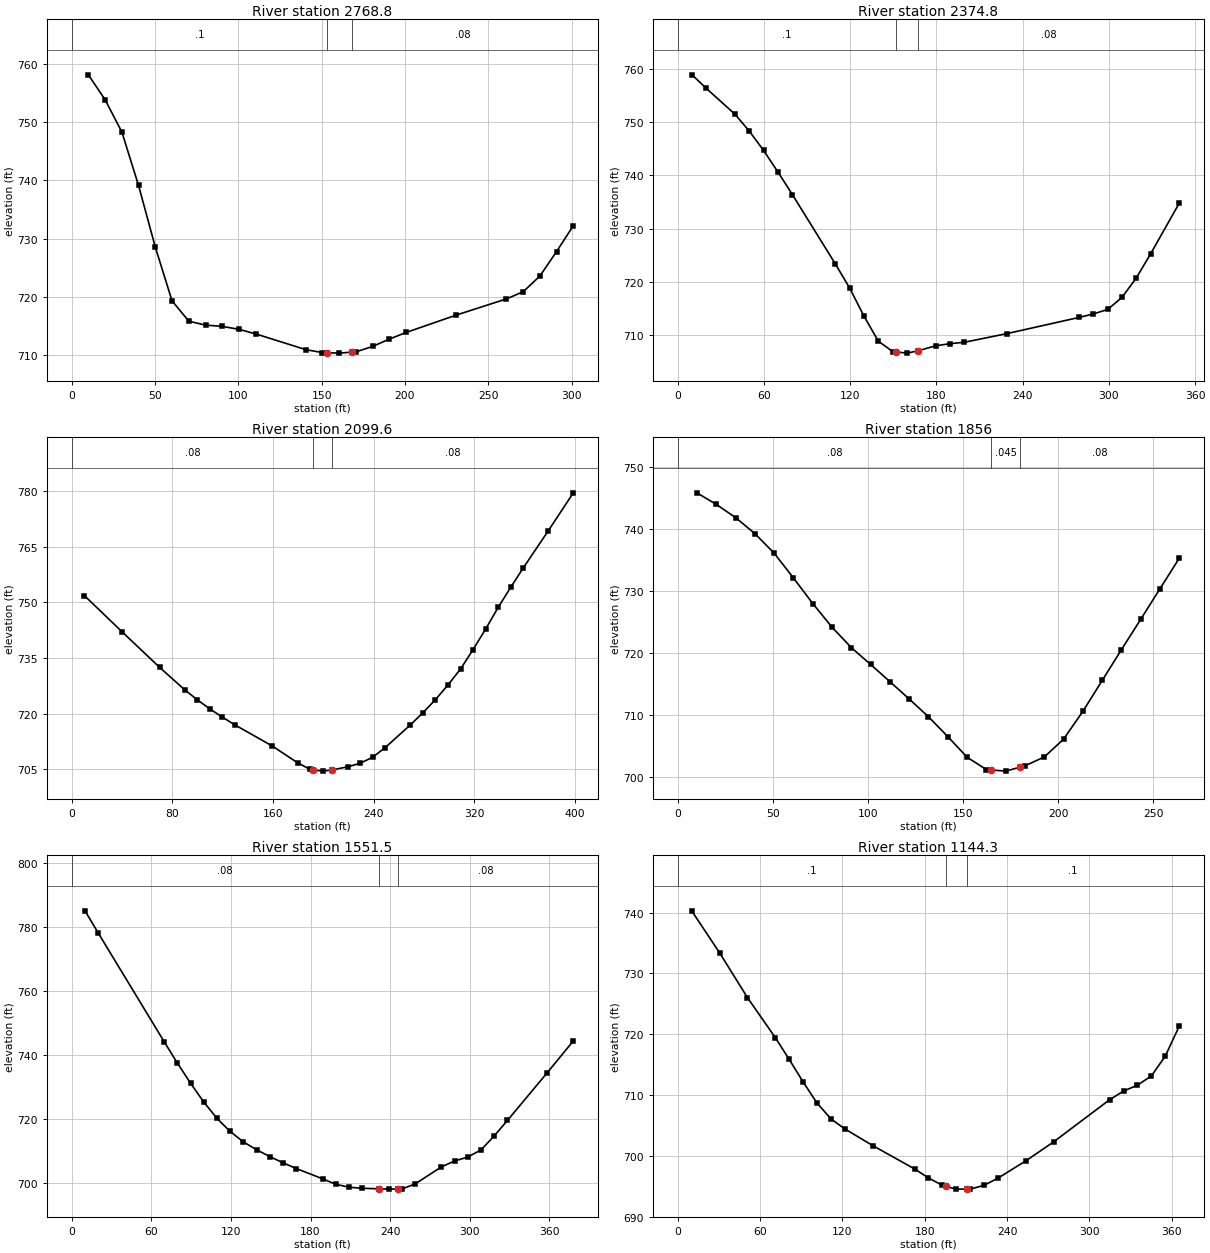
Type RM Length L Ch R = 1 ,2768.8  ,402.9,394.1,382.5
XS GIS Cut Line= 2
     1559862.989      375874.144     1559965.247       376157.32
#Sta/Elev= 26
      10  758.15    20.1  753.83    30.1  748.31    40.1  739.13    50.2  728.49
    60.2  719.29    70.3  715.79    80.3  715.12    90.3   714.9   100.4  714.39
   110.4  713.61   140.5   710.9   150.5  710.39   153.1  710.37   160.6   710.3
   168.1  710.47   170.6  710.52   180.6  711.45   190.7  712.72   200.7  713.85
   230.8  716.84   260.9  719.62     271  720.86     281  723.55     291  727.75
   301.1  732.22
#Mann= 3 , 0 , 0
       0      .1       0   153.1    .045       0   168.1     .08       0
Bank Sta=153.1,168.1
XS Rating Curve= 0 ,0
Exp/Cntr=0.3,0.1

Type RM Length L Ch R = 1 ,2374.8  ,271.9,275.2,278.4
XS GIS Cut Line= 2
     1559487.387      376068.827     1559735.166      376314.639
#Sta/Elev= 26
      10  758.94    19.9  756.39    39.9  751.52    49.9  748.32    59.8  744.71
    69.8  740.64    79.8  736.42   109.7  723.36   119.7  718.81   129.6  713.55
   139.6  708.83   149.6  706.87   152.1   706.8   159.6  706.58   167.1  707.01
   179.5  707.96   189.5  708.36   199.4  708.62   229.4  710.27   279.2  713.29
   289.2  713.95   299.2   714.8   309.1  717.06   319.1  720.72   329.1  725.28
     349   734.8
#Mann= 3 , 0 , 0
       0      .1       0   152.1    .045       0   167.1     .08       0
Bank Sta=152.1,167.1
XS Rating Curve= 0 ,0
Exp/Cntr=0.3,0.1

Type RM Length L Ch R = 1 ,2099.6  ,245,243.6,242.2
XS GIS Cut Line= 2
     1559280.905      376210.415     1559520.818      376528.988
#Sta/Elev= 30
      10  751.82    39.9  742.08    69.8  732.49    89.7  726.45    99.7  723.76
   109.7  721.31   119.6  719.08   129.6  716.99   159.5  711.27   179.5  706.77
   189.4  704.99   191.9  704.87   199.4  704.51   206.9  704.82   219.3  705.67
   229.3  706.62   239.3  708.27   249.3  710.87   269.2  716.96   279.2  720.24
   289.1  723.74   299.1  727.72   309.1  732.01     319  737.21     329  742.75
     339   748.6     349  754.03   358.9  759.21   378.9  769.28   398.8  779.49
#Mann= 3 , 0 , 0
       0     .08       0   191.9    .045       0   206.9     .08       0
Bank Sta=191.9,206.9
XS Rating Curve= 0 ,0
Exp/Cntr=0.3,0.1

Type RM Length L Ch R = 1 ,1856    ,301.1,304.5,307.8
XS GIS Cut Line= 2
      1559109.82      376403.132     1559280.905      376603.715
#Sta/Elev= 28
    10.1  745.83    20.3  743.96    30.4  741.84    40.6  739.24    50.7  736.09
    60.8  732.11      71  727.96    81.1  724.15    91.3  720.84   101.4  718.13
   111.5  715.37   121.7  712.55   131.8  709.69     142  706.48   152.1  703.16
   162.2  701.18   164.9  701.11   172.4  700.92   179.9  701.56   182.5  701.78
   192.7  703.21   202.8  706.08   212.9  710.55   223.1  715.55   233.2  720.52
   243.4  725.45   253.5  730.37   263.6  735.28
#Mann= 3 , 0 , 0
       0     .08       0   164.9    .045       0   179.9     .08       0
Bank Sta=164.9,179.9
XS Rating Curve= 0 ,0
Exp/Cntr=0.3,0.1

Type RM Length L Ch R = 1 ,1551.5  ,417.1,407.2,397.3
XS GIS Cut Line= 2
     1558848.275       376505.39     1559048.858      376825.929
#Sta/Elev= 30
      10  785.01    19.9  778.14    69.7  744.17    79.6  737.55    89.6  731.21
    99.5   725.4   109.5  720.27   119.4   716.2   129.4  712.95   139.3  710.51
   149.3  708.37   159.2  706.44   169.2  704.65   189.1  701.44     199  699.74
     209  698.81   218.9  698.49   231.3  698.32   238.8  698.22   246.3  698.25
   248.8  698.26   258.7   699.8   278.6  705.14   288.6     707   298.5  708.22
   308.5  710.45   318.4  714.78   328.4  719.63   358.2  734.41   378.1  744.45
#Mann= 3 , 0 , 0
       0     .08       0   231.3    .045       0   246.3     .08       0
Bank Sta=231.3,246.3
XS Rating Curve= 0 ,0
Exp/Cntr=0.3,0.1

Type RM Length L Ch R = 1 ,1144.3  ,220.8,217.7,216.3
XS GIS Cut Line= 2
     1558529.702      376745.303     1558836.476      376943.919
#Sta/Elev= 27
    10.2  740.28    30.5   733.4    50.8  726.04    71.1  719.46    81.2   715.9
    91.4  712.17   101.5  708.71   111.7   706.1   121.8  704.45   142.1  701.72
   172.6  697.88   182.7  696.41   192.9  695.17   195.5  695.01     203  694.56
   210.5  694.57   213.2  694.57   223.3  695.19   233.5  696.38   253.8  699.22
   274.1  702.35   314.7  709.24   324.9  710.67     335  711.63   345.2  713.16
   355.3  716.41   365.5  721.35
#Mann= 3 , 0 , 0
       0      .1       0   195.5    .045       0   210.5      .1       0
Bank Sta=195.5,210.5
XS Rating Curve= 0 ,0
Exp/Cntr=0.3,0.1

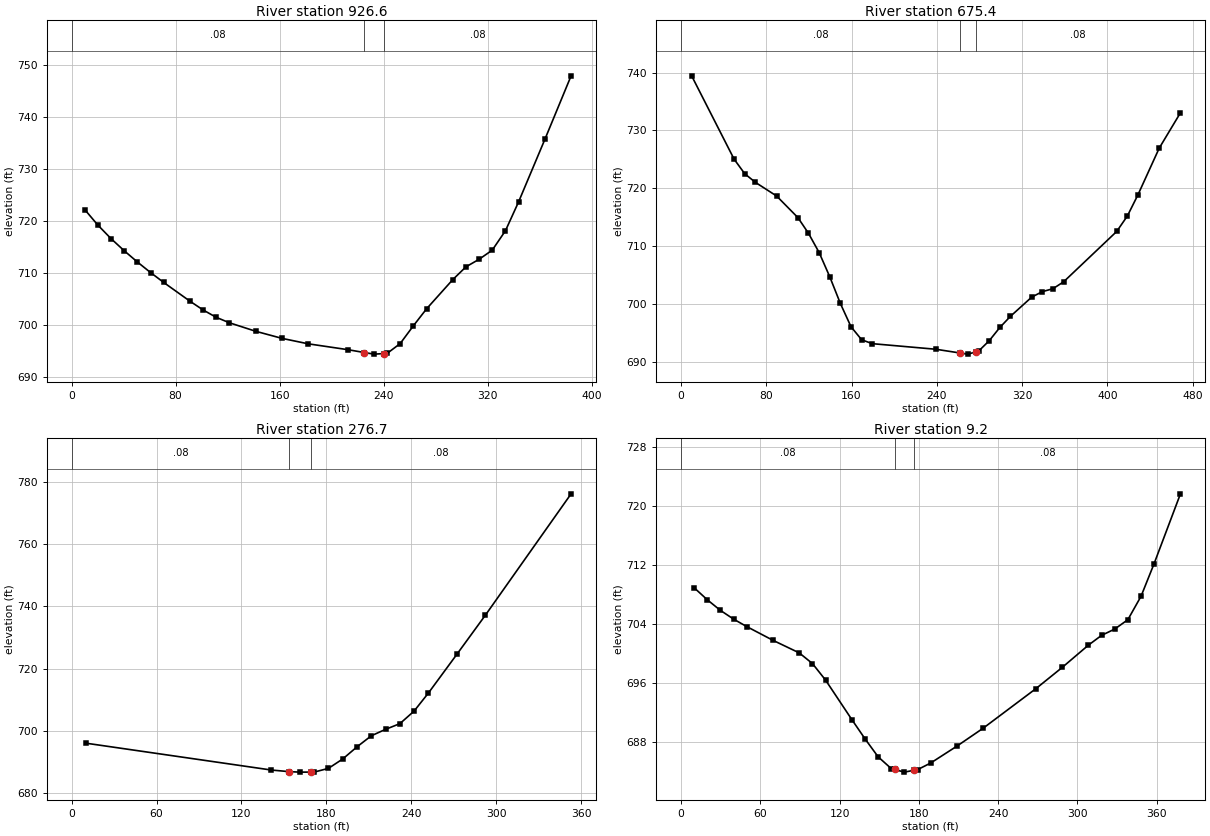
Type RM Length L Ch R = 1 ,926.6   ,248.5,251.2,254
XS GIS Cut Line= 2
     1558409.746      376934.087     1558753.883      377105.172
#Sta/Elev= 30
    10.1  722.14    20.2  719.16    30.3  716.57    40.5  714.23    50.6  712.08
    60.7  710.06    70.8  708.16      91  704.56   101.1  702.88   111.3  701.45
   121.4  700.41   141.6  698.78   161.8  697.42     182  696.37   212.4  695.25
   225.1   694.7   232.6  694.39   240.1  694.49   242.7  694.52   252.8  696.42
     263  699.85   273.1  703.09   293.3  708.71   303.4  711.15   313.5   712.6
   323.6  714.35   333.8  718.09   343.9  723.63   364.1  735.62   384.3  747.83
#Mann= 3 , 0 , 0
       0     .08       0   225.1    .045       0   240.1     .08       0
Bank Sta=225.1,240.1
XS Rating Curve= 0 ,0
Exp/Cntr=0.3,0.1

Type RM Length L Ch R = 1 ,675.4   ,390,398.7,400.3
XS GIS Cut Line= 2
     1558249.945      377083.187     1558641.279      377340.798
#Sta/Elev= 30
      10  739.45    49.8  725.05    59.8  722.52    69.8  721.03    89.7  718.67
   109.7  714.93   119.6  712.22   129.6  708.89   139.6  704.69   149.5  700.09
   159.5  696.06   169.5  693.81   179.4  693.14   239.2  692.17   261.6  691.53
   269.1  691.33   276.6  691.71   279.1  691.84   289.1  693.64   299.1  695.94
     309  697.86     329  701.19   338.9  702.13   348.9  702.64   358.9  703.83
   408.7  712.54   418.7  715.21   428.6  718.86   448.6  726.95   468.5  733.06
#Mann= 3 , 0 , 0
       0     .08       0   261.6    .045       0   276.6     .08       0
Bank Sta=261.6,276.6
XS Rating Curve= 0 ,0
Exp/Cntr=0.3,0.1

Type RM Length L Ch R = 1 ,276.7   ,262.9,267.6,271.9
XS GIS Cut Line= 2
     1558066.474      377277.098     1558269.023      377566.174
#Sta/Elev= 17
    10.1  696.06   141.2  687.44   153.9  686.92   161.4  686.77   168.9  686.78
   171.4  686.78   181.5  687.98   191.6  690.99   201.7  694.89   211.8  698.44
   221.9  700.51     232  702.33     242  706.35   252.1  712.13   272.3  724.61
   292.5   737.2     353   776.1
#Mann= 3 , 0 , 0
       0     .08       0   153.9    .045       0   168.9     .08       0
Bank Sta=153.9,168.9
XS Rating Curve= 0 ,0
Exp/Cntr=0.3,0.1

Type RM Length L Ch R = 1 ,9.2     ,0,9.2,21.4
XS GIS Cut Line= 2
     1557855.546      377299.038     1557998.775      377648.864
#Sta/Elev= 29
     9.9   708.9    19.9  707.26    29.8  705.82    39.8  704.63    49.7  703.62
    69.6  701.75    89.5  700.04    99.5  698.59   109.4  696.35   129.3  690.98
   139.3  688.36   149.2  685.92   159.2  684.31   161.6   684.2   169.1  683.84
   176.6   684.1   179.1  684.18     189  685.08   208.9  687.38   228.8  689.82
   268.6  695.18   288.5  698.06   308.4   701.1   318.3  702.42   328.3  703.28
   338.2  704.55   348.2  707.74   358.1  712.18     378  721.65
#Mann= 3 , 0 , 0
       0     .08       0   161.6    .045       0   176.6     .08       0
Bank Sta=161.6,176.6
XS Rating Curve= 0 ,0
Exp/Cntr=0.3,0.1

Chan Stop Cuts=-1
Use User Specified Reach Order=0